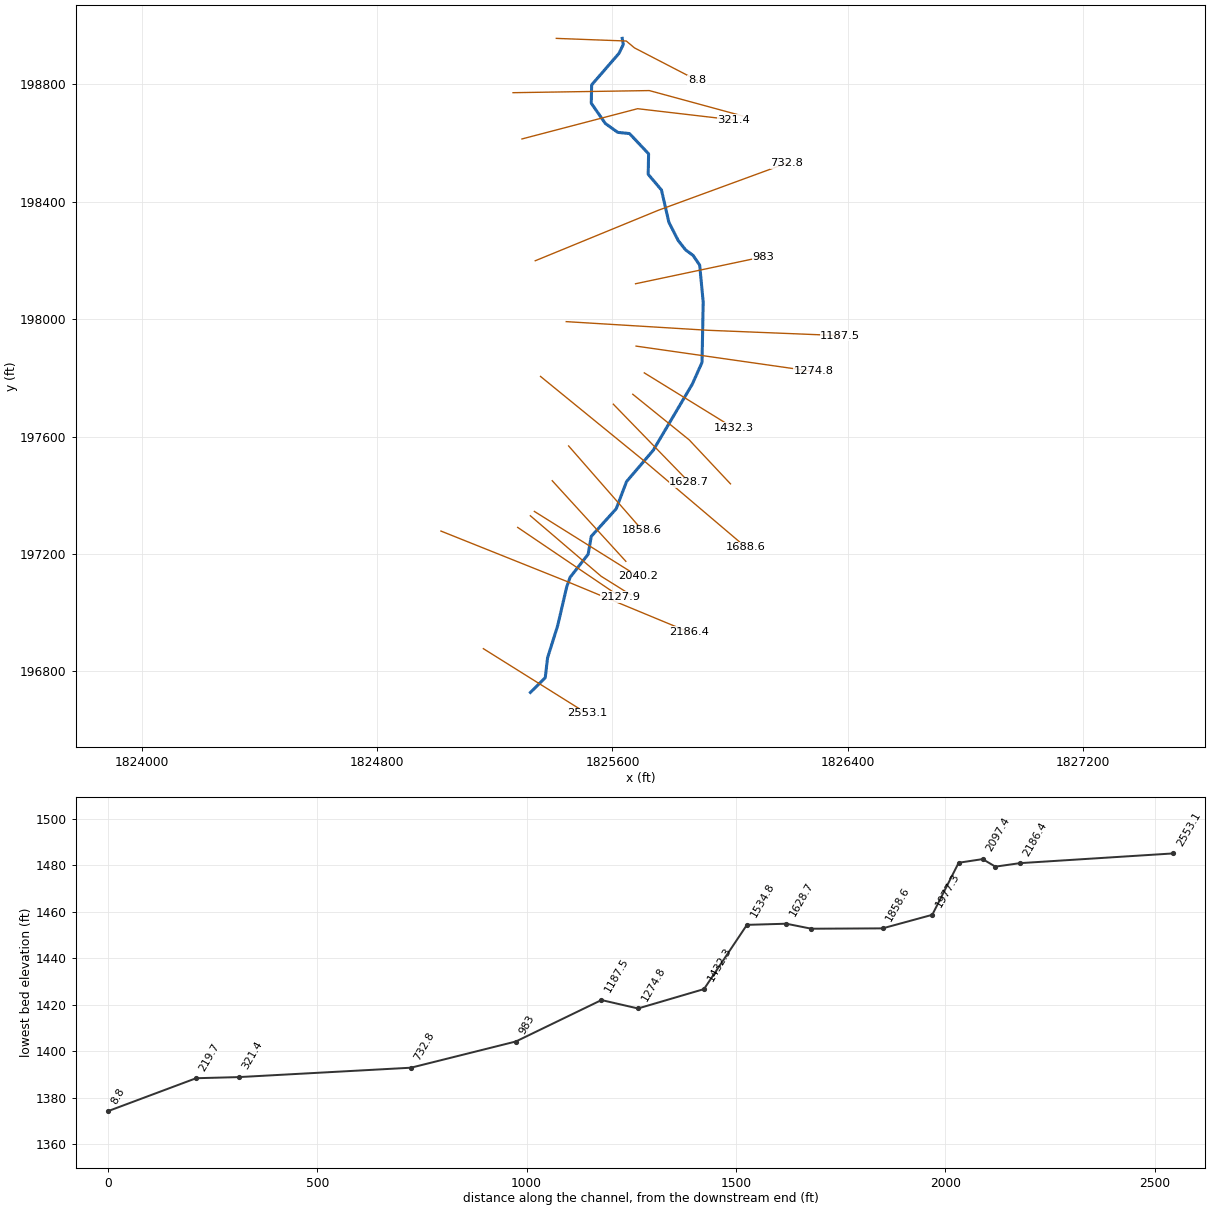
--- SmithBr.prj (project) ---

Proj Title=SmithBr
Current Plan=p01
Default Exp/Contr=0,0
English Units
Geom File=g01
Flow File=f01
Plan File=p01
BEGIN DESCRIPTION:
END DESCRIPTION:
DSS Export Rating Curves= 0
DSS Export Rating Curve Sorted= 0
DSS Export Volume Flow Curves= 0
DXF OffsetX= 0
DXF OffsetY= 0
DXF ScaleX= 0
DXF ScaleY= 0

--- SmithBr.p01 (plan) ---

Plan Title=Floodplain
Program Version=4.00
Geom File=g01
Flow File=f01
K Sum by GR=0
Std Step Tol=0.01
Critical Tol=0.01
Num of Std Step Trials=20
Max Error Tol=0.3
Flow Tol Ratio=0.001
Split Flow NTrial=30
Split Flow Tol=0.02
Split Flow Ratio=0.02
Log Output Level=0
Friction Slope Method=1
Unsteady Friction Slope Method=2
Unsteady Bridges Friction Slope Method=1
Global Log Level=0
CheckData=False
Run HTab=0
Run UNet=0
Run PostProcess=0
UNET Theta=0
UNET Theta Warmup=0
UNET ZTol=0
UNET ZSATol=0
UNET MxIter=0
UNET MaxInSteps=0
UNET DtIC=0
UNET DtMin=0
UNET MaxCRTS=0
UNET WFStab=0
UNET SFStab=0
UNET WFX=0
UNET SFX=0
UNET DSS MLevel=0
UNET DZMax Abort=0
UNET Convert EG Bridges=0
UNET Use Existing IB Tables=0
UNET Froude Limit=0
UNET Froude Power=0
Write IC File=0
Echo Input=False
Echo Output=False
Write Detailed=0

--- SmithBr.f01 (steady flow) ---

Flow Title=NFF Regression Equation
Program Version=4.00
Number of Profiles=1
Profile Names=P100yr
River Rch & RM=SmithBr,Main      ,2553.1
552.2681
River Rch & RM=SmithBr,Main      ,1432.3
562.6782
River Rch & RM=SmithBr,Main      ,1187.5
638.6045
River Rch & RM=SmithBr,Main      ,321.4
651.9412
Boundary for River Rch & Prof#=SmithBr,Main      ,1
Up Type=0
Dn Type=3
Dn Slope=0.027155

--- SmithBr.g01 (geometry) ---

Geom Title=USGS 10m DEM
Program Version=4.00

River Reach=SmithBr         ,Main
Reach XY= 30
      1825320.97       196728.17     1825371.366      196778.566
     1825379.323      196846.203     1825413.805       196956.28
     1825444.308      197087.576     1825455.927      197120.496
      1825517.25      197198.978      1825527.86      197259.984
     1825612.738      197354.146     1825647.741      197446.556
     1825738.616      197553.414     1825871.351      197778.536
     1825904.506      197852.804     1825908.485      198058.368
     1825896.549      198184.359     1825874.003      198217.515
     1825848.805      198236.082     1825823.607      198267.911
     1825791.778      198330.243     1825766.579       198440.32
     1825721.488      198493.718     1825722.814      198563.658
      1825657.83      198632.622     1825618.043        198636.6
     1825575.604      198667.103      1825527.86      198736.067
     1825529.186      198798.399     1825622.022      198905.823
     1825636.727      198935.899     1825633.195      198957.097

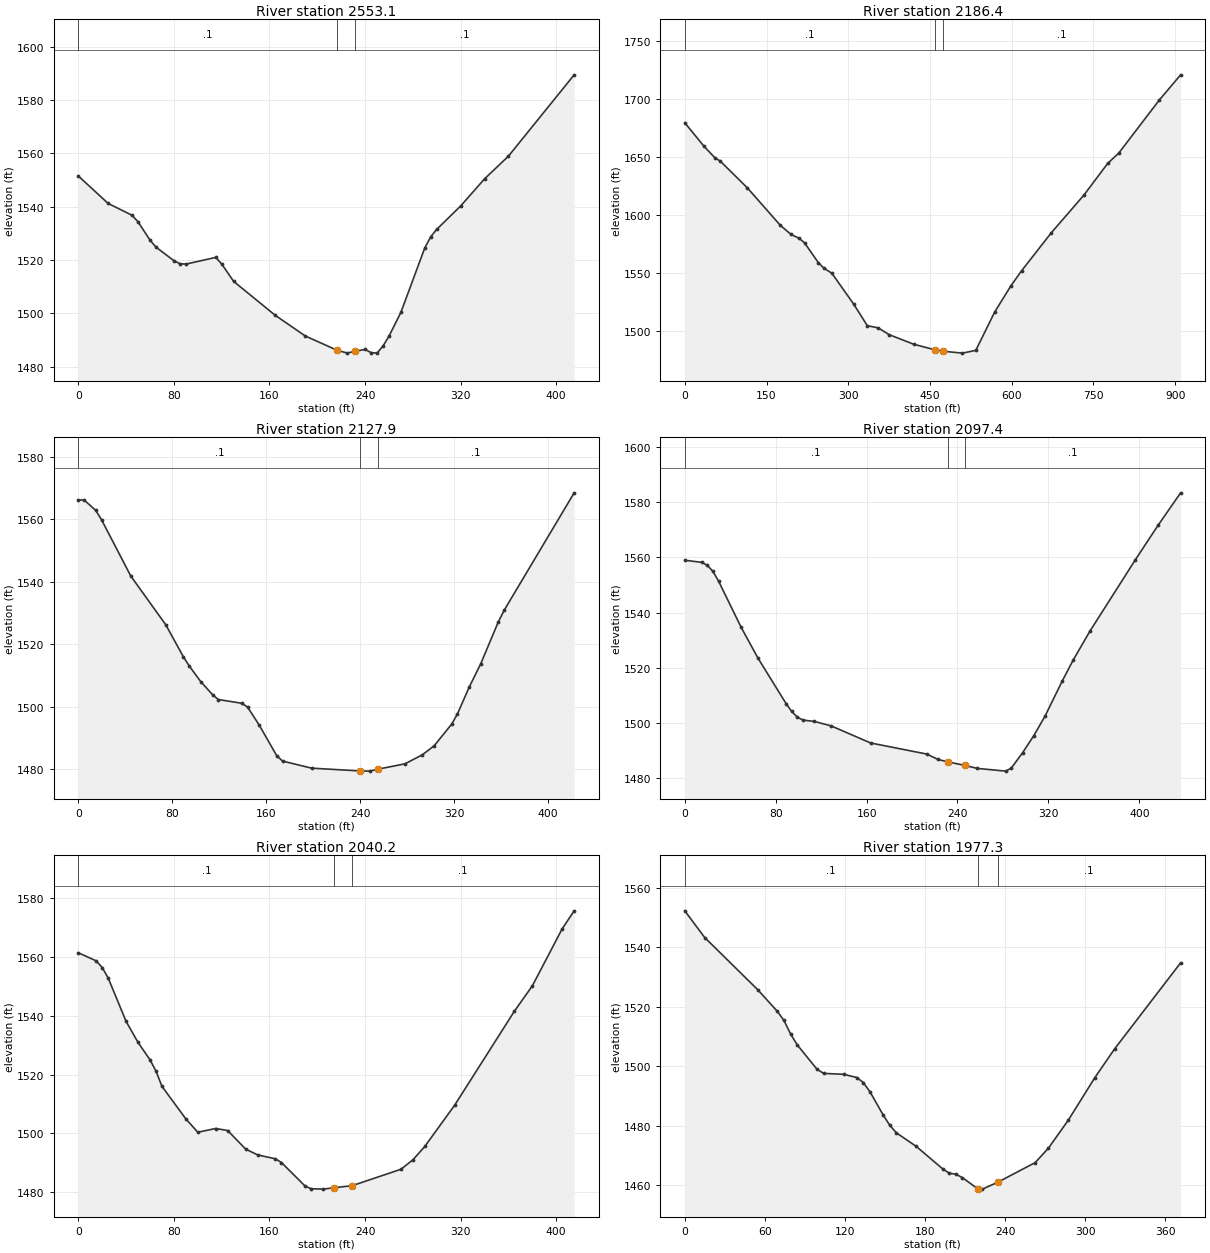
Type RM Length L Ch R = 1 ,2553.1  ,363.3,366.7,370
XS GIS Cut Line= 2
     1825160.996      196877.348     1825512.548      196656.863
#Sta/Elev= 30
       0 1551.52      25 1541.22      45 1536.78      50 1534.32      60 1527.46
      65 1524.85      80 1519.76      85 1518.63      90 1518.47     115 1520.99
     120 1518.52     130 1511.99     165 1499.21     190 1491.51   216.7 1486.14
     225 1485.14   231.7 1485.77     240 1486.48     245 1485.28     250 1485.09
     255 1487.74     260 1491.44     270  1500.4     290 1524.58     295 1528.77
     300 1531.53     320 1540.28     340 1550.46     360 1558.97     415 1589.47
#Mann= 3 , 0 , 0
       0      .1       0   216.7    .045       0   231.7      .1       0
Bank Sta=216.7,231.7
XS Rating Curve= 0 ,0
Exp/Cntr=0.3,0.1

Type RM Length L Ch R = 1 ,2186.4  ,63.1,58.4,53.9
XS GIS Cut Line= 3
     1825016.675      197278.136     1825438.998      197108.838
     1825859.232       196934.29
#Sta/Elev= 30
       0 1679.75      35 1659.61      55 1649.62      65 1646.69     115 1623.48
     175 1591.37     195 1583.36     210    1580     220 1575.97     245 1559.08
     255 1554.36     270  1549.8     310 1523.19     335 1504.58     355  1502.7
     375 1496.85     420  1488.6   459.6 1483.69   474.6 1482.52   509.4  1480.9
   534.1 1483.29   568.8 1516.42   598.4 1538.92   618.2 1552.05   672.6 1584.76
     732 1617.04   776.5 1644.87   796.3 1653.46   870.5 1699.18     910 1721.15
#Mann= 3 , 0 , 0
       0      .1       0   459.6    .045       0   474.6      .1       0
Bank Sta=459.6,474.6
XS Rating Curve= 0 ,0
Exp/Cntr=0.3,0.1

Type RM Length L Ch R = 1 ,2127.9  ,33.1,30.5,27.9
XS GIS Cut Line= 2
     1825277.673      197290.554     1825627.169      197053.505
#Sta/Elev= 30
       0 1566.18       5 1566.11    14.9 1562.78    19.9 1559.72    44.7 1541.79
    74.5 1526.21    89.4 1516.02    94.4 1513.07   104.3 1508.02   114.3 1503.85
   119.2 1502.31   139.1 1501.12   144.1 1499.91     154 1494.16   168.9 1484.39
   173.9 1482.62   198.7 1480.35   240.2 1479.45   248.4  1479.4   255.2 1480.03
   278.2 1481.73   293.1 1484.65   303.1 1487.52     318 1494.45   322.9  1497.7
   332.9 1506.27   342.8  1513.8   357.7 1527.13   362.7 1530.87   422.3 1568.43
#Mann= 3 , 0 , 0
       0      .1       0   240.2    .045       0   255.2      .1       0
Bank Sta=240.2,255.2
XS Rating Curve= 0 ,0
Exp/Cntr=0.3,0.1

Type RM Length L Ch R = 1 ,2097.4  ,54.2,57.2,60.2
XS GIS Cut Line= 3
     1825320.717      197330.275     1825561.546      197124.027
     1825662.625      197060.596
#Sta/Elev= 30
       0 1558.95    14.9 1558.18    19.8 1557.12    24.8 1554.88    29.7 1551.42
    49.5 1534.75    64.4 1523.53    89.2 1507.04    94.1 1504.23    99.1 1502.15
     104 1501.11     114 1500.62   128.8 1499.01   163.5 1492.83     213 1488.81
   222.9 1486.86   231.3 1486.01   246.3 1484.72   257.6 1483.62   282.4 1482.64
   287.4 1483.74   297.3  1489.3   307.2 1495.49   317.1 1502.56     332 1515.08
   341.9 1522.88   356.8 1533.44   396.6 1559.14   416.5 1571.56   436.4 1583.34
#Mann= 3 , 0 , 0
       0      .1       0   231.3    .045       0   246.3      .1       0
Bank Sta=231.3,246.3
XS Rating Curve= 0 ,0
Exp/Cntr=0.3,0.1

Type RM Length L Ch R = 1 ,2040.2  ,69,63,57
XS GIS Cut Line= 2
     1825334.387      197345.079      1825685.94      197124.595
#Sta/Elev= 30
       0 1561.42      15 1558.66      20 1556.38      25 1552.81      40 1538.08
      50 1530.93      60 1525.03      65 1521.19      70 1516.01      90 1504.93
     100 1500.41     115 1501.68     125 1500.99     140 1494.69     150 1492.72
     165 1491.37     170 1490.12     190 1482.03     195  1481.2     205 1481.07
   214.2 1481.55   229.2 1482.24     270 1487.82     280 1491.01     290 1495.59
     315 1509.61     365 1541.57     380 1550.18     405 1569.58     415 1575.68
#Mann= 3 , 0 , 0
       0      .1       0   214.2    .045       0   229.2      .1       0
Bank Sta=214.2,229.2
XS Rating Curve= 0 ,0
Exp/Cntr=0.3,0.1

Type RM Length L Ch R = 1 ,1977.3  ,120.3,118.7,117.1
XS GIS Cut Line= 2
     1825395.185      197449.599     1825645.403      197175.068
#Sta/Elev= 30
       0 1552.27    14.9  1543.3    54.5 1525.81    69.3 1518.48    74.3  1515.4
    79.2 1510.89    84.2 1507.22      99 1499.02     104 1497.61   118.9 1497.31
   128.8 1496.23   133.7 1494.53   138.7 1491.44   148.6 1483.61   153.5  1480.2
   158.5 1477.62   173.3 1473.09   193.2  1465.5   198.1 1464.05   203.1 1463.72
     208 1462.54   219.3 1458.86   222.9  1458.7   234.3 1460.98   262.5 1467.63
   272.4 1472.49   287.3 1481.91   307.1 1496.16   321.9 1505.82   371.4 1534.79
#Mann= 3 , 0 , 0
       0      .1       0   219.3    .045       0   234.3      .1       0
Bank Sta=219.3,234.3
XS Rating Curve= 0 ,0
Exp/Cntr=0.3,0.1

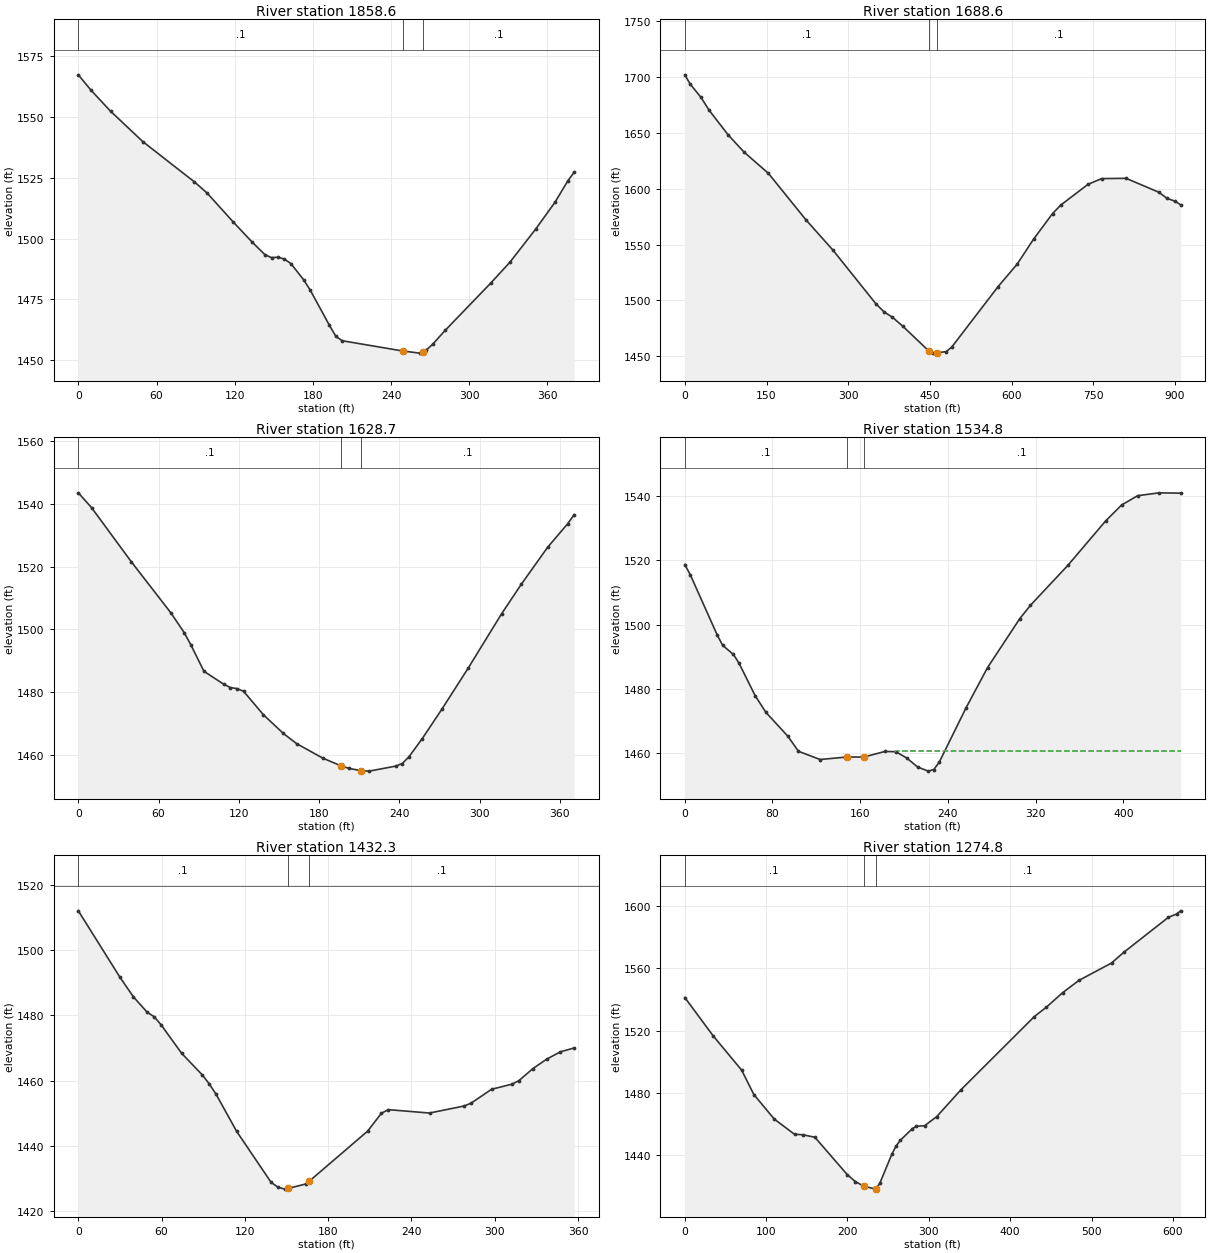
Type RM Length L Ch R = 1 ,1858.6  ,164.9,169.9,174.5
XS GIS Cut Line= 2
     1825450.901      197568.124      1825701.12      197281.436
#Sta/Elev= 30
       0 1567.37     9.9 1560.93    24.7 1552.43    49.4 1539.93      89 1523.36
    98.8 1518.75   118.6 1506.99   133.4 1498.54   143.3 1493.32   148.3 1492.16
   153.2 1492.34   158.1 1491.55   163.1 1489.72     173 1482.98   177.9 1478.85
   192.7  1464.3   197.7 1459.72   202.6 1457.96   249.2 1453.73   261.9 1452.87
   264.2 1453.42   266.9 1454.07   271.8 1456.46   281.7 1462.34   316.3 1481.58
   331.1  1490.2   350.9 1503.86   365.7 1514.87   375.6 1523.72   380.5 1527.31
#Mann= 3 , 0 , 0
       0      .1       0   249.2    .045       0   264.2      .1       0
Bank Sta=249.2,264.2
XS Rating Curve= 0 ,0
Exp/Cntr=0.3,0.1

Type RM Length L Ch R = 1 ,1688.6  ,62.7,60,57.7
XS GIS Cut Line= 3
     1825355.296      197805.042     1825707.727      197517.092
     1826054.322      197222.339
#Sta/Elev= 30
       0    1702     9.9 1693.74    29.7 1681.78    44.5 1670.39    79.2 1648.45
   108.8 1632.79   153.4 1613.79   222.6 1571.98   272.1 1544.89   351.2 1496.67
   366.1 1489.51   380.9 1484.96   400.7 1476.59   447.6 1454.77   455.1 1452.72
   462.6    1453   480.1  1454.1   490.1 1458.23   575.1 1512.34   610.1 1532.46
   640.1 1554.75   675.1 1577.77   690.1 1585.34   740.1 1603.92   765.1 1609.04
   810.1 1609.29   870.1 1596.83   885.1 1591.39   900.1 1588.74   910.1 1585.56
#Mann= 3 , 0 , 0
       0      .1       0   447.6    .045       0   462.6      .1       0
Bank Sta=447.6,462.6
XS Rating Curve= 0 ,0
Exp/Cntr=0.3,0.1

Type RM Length L Ch R = 1 ,1628.7  ,91.1,93.9,96.7
XS GIS Cut Line= 2
     1825602.856      197710.455     1825860.841      197444.365
#Sta/Elev= 30
       0 1543.48     9.9 1538.76    39.5 1521.58    69.2 1505.25    79.1 1498.99
      84 1495.18    93.9 1486.65   108.7 1482.54   113.7 1481.47   118.6 1481.15
   123.5  1480.3   138.4 1472.79   153.2 1466.89   163.1 1463.64   182.8 1458.99
   196.5 1456.52   202.6 1455.71   211.5 1455.01   217.4 1454.87   237.2 1456.47
   242.1 1457.29   247.1 1459.42     257 1465.19   271.8 1474.64   291.6  1487.8
   316.3 1504.93   331.1 1514.38   350.8 1526.16   365.7 1533.61   370.6 1536.52
#Mann= 3 , 0 , 0
       0      .1       0   196.5    .045       0   211.5      .1       0
Bank Sta=196.5,211.5
XS Rating Curve= 0 ,0
Exp/Cntr=0.3,0.1

Type RM Length L Ch R = 1 ,1534.8  ,99.6,102.5,105.4
XS GIS Cut Line= 3
      1825669.04      197744.222     1825860.841      197588.891
     1826001.314      197438.963
#Sta/Elev= 30
       0 1518.74     4.9 1515.62    29.6 1496.77    34.6 1493.54    44.4 1490.72
    49.4 1488.04    64.2 1477.87      74 1472.68    93.8 1465.34   103.7 1460.56
   123.4    1458   148.2 1458.79   163.2 1458.76   182.6 1460.51   192.5 1460.43
   202.4 1458.48   212.3 1455.68   222.1 1454.38   227.1 1454.88     232  1457.1
   256.6 1474.12   276.2 1486.65   305.5 1501.84   315.3 1506.04   349.5  1518.5
   383.8 1532.28   398.4 1537.26   413.1 1540.18   432.7 1541.07   452.3 1540.97
#Mann= 3 , 0 , 0
       0      .1       0   148.2    .045       0   163.2      .1       0
#XS Ineff= 2 , 0
                          191.98         1460.73
Permanent Ineff=
       F       F
Bank Sta=148.2,163.2
XS Rating Curve= 0 ,0
Exp/Cntr=0.3,0.1

Type RM Length L Ch R = 1 ,1432.3  ,148.2,157.5,166.9
XS GIS Cut Line= 2
     1825708.211      197817.161      1826012.12      197629.412
#Sta/Elev= 30
       0 1512.06    29.8 1491.82    39.7 1485.69    49.6 1480.98    54.6 1479.61
    59.5  1477.2    74.4 1468.41    89.3 1461.78    94.3 1459.04    99.2 1455.87
   114.1 1444.44   138.9 1428.84   143.9 1427.34   148.8 1426.77   151.1 1426.98
   163.7 1428.33   166.1 1429.11   208.4 1444.54   218.3    1450   223.3 1451.13
     253 1450.09   277.8 1452.24   282.8 1453.08   297.7 1457.37   312.6 1458.96
   317.5 1460.06   327.5 1463.72   337.4  1466.6   347.3 1468.86   357.2 1470.03
#Mann= 3 , 0 , 0
       0      .1       0   151.1    .045       0   166.1      .1       0
Bank Sta=151.1,166.1
XS Rating Curve= 0 ,0
Exp/Cntr=0.3,0.1

Type RM Length L Ch R = 1 ,1274.8  ,85.4,87.3,89.2
XS GIS Cut Line= 2
     1825680.296      197908.333     1826283.612      197821.888
#Sta/Elev= 30
       0 1541.16      35 1516.52    69.9 1494.62    84.9 1479.03   109.9 1463.34
   134.9 1453.56   144.9 1453.28   159.9 1451.66   199.8 1427.69   209.8 1423.22
   219.8  1420.4   234.8 1418.44   239.8 1422.27   254.8 1441.19   259.8  1446.1
   264.8 1449.66   279.8 1457.22   284.8 1458.71   294.8 1459.04   309.7 1464.89
   339.7 1482.21   429.6 1528.92   444.6 1535.02   464.6 1544.31   484.6 1552.16
   524.6 1563.26   539.5 1570.05   594.5 1592.54   604.5 1594.62   609.5 1596.67
#Mann= 3 , 0 , 0
       0      .1       0   219.8    .045       0   234.8      .1       0
Bank Sta=219.8,234.8
XS Rating Curve= 0 ,0
Exp/Cntr=0.3,0.1

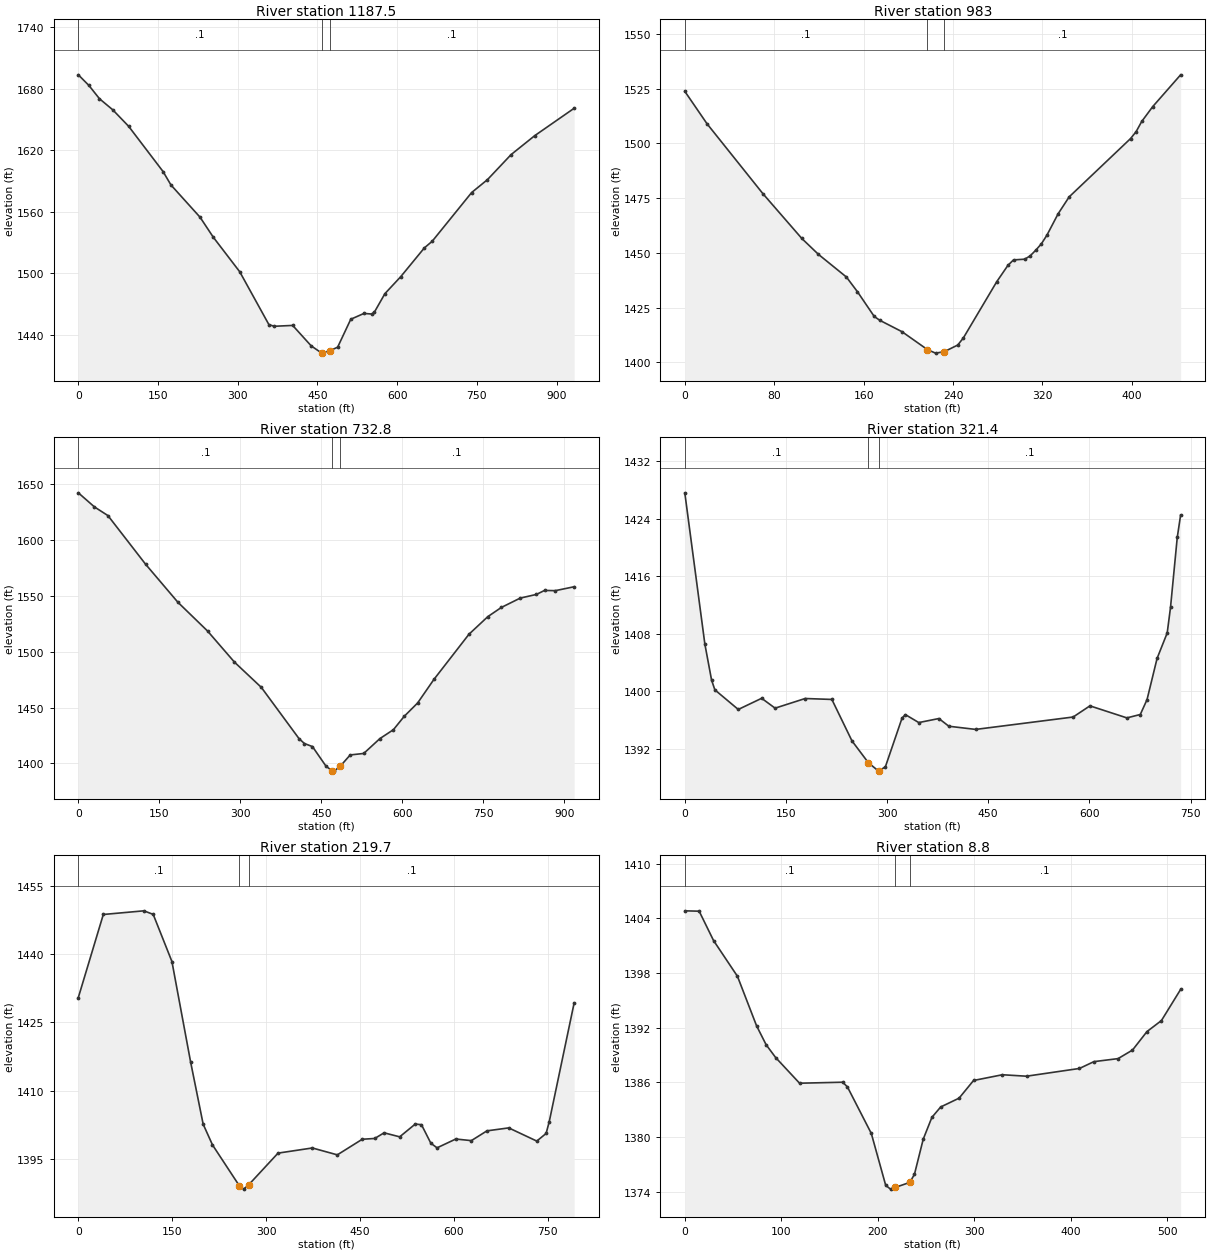
Type RM Length L Ch R = 1 ,1187.5  ,198.4,204.5,210.5
XS GIS Cut Line= 3
     1825442.782      197991.741     1825924.943      197962.275
     1826374.624      197944.106
#Sta/Elev= 30
       0 1693.33    19.9 1682.98    39.8 1670.02    64.7 1659.27    94.6 1643.21
   159.4 1599.09   174.3 1585.97   229.1 1554.52     254 1535.03   303.8 1501.32
   358.6 1449.88   368.5 1448.23   403.4 1449.06   438.2 1429.15   458.1 1422.06
   473.1 1424.34     488 1427.86   512.7 1455.08   537.5 1460.74   552.3 1460.18
   557.2 1462.06     577 1480.06   606.7 1496.56   651.2 1524.63     666 1531.12
   740.2  1578.6   769.9 1591.14   814.4 1615.56   858.9 1634.03   933.1 1660.74
#Mann= 3 , 0 , 0
       0      .1       0   458.1    .045       0   473.1      .1       0
Bank Sta=458.1,473.1
XS Rating Curve= 0 ,0
Exp/Cntr=0.3,0.1

Type RM Length L Ch R = 1 ,983     ,246.8,250.3,253.7
XS GIS Cut Line= 2
     1825678.495      198120.844     1826112.523      198212.693
#Sta/Elev= 30
       0 1523.74    19.9 1508.92    69.8 1477.07   104.7 1456.57   119.6  1449.3
   144.6 1438.97   154.5 1432.24   169.5 1420.97   174.5 1419.21   194.4    1414
     217 1405.87   224.3 1404.24     232 1404.87   244.2 1407.93   249.2 1411.16
   279.1 1436.85   289.1 1444.31   294.1 1446.79   304.1 1447.12     309 1448.63
     314 1451.23     319 1454.12     324  1458.1     334 1467.84   343.9 1475.57
   398.8 1502.17   403.8 1505.34   408.8 1509.98   418.7  1516.8   443.6 1531.27
#Mann= 3 , 0 , 0
       0      .1       0     217    .045       0     232      .1       0
Bank Sta=217,232
XS Rating Curve= 0 ,0
Exp/Cntr=0.3,0.1

Type RM Length L Ch R = 1 ,732.8   ,421.6,411.3,409.3
XS GIS Cut Line= 3
     1825337.383      198199.161     1825756.882      198371.602
     1826193.083      198531.811
#Sta/Elev= 30
       0 1642.44    29.9 1629.78    54.8 1622.04   124.6 1578.41   184.4 1544.33
   239.2 1518.62   289.1  1490.7   338.9 1468.04   408.7 1422.11   418.7 1417.72
   433.6 1414.97   458.6 1397.46   470.2 1393.15   473.6 1392.98   485.2 1397.48
   503.5 1407.49   528.5 1408.82   558.5 1422.16   583.5 1430.12   603.5  1442.1
   628.4 1454.11   658.4 1475.13   723.4 1515.68   758.4 1531.49   783.3 1539.68
   818.3 1548.07   848.3 1551.37   863.3 1554.94   883.3 1554.75   918.2 1558.25
#Mann= 3 , 0 , 0
       0      .1       0   470.2    .045       0   485.2      .1       0
Bank Sta=470.2,485.2
XS Rating Curve= 0 ,0
Exp/Cntr=0.3,0.1

Type RM Length L Ch R = 1 ,321.4   ,107.1,101.7,96.3
XS GIS Cut Line= 3
     1825292.228      198614.248     1825685.462      198717.344
     1826011.995      198679.221
#Sta/Elev= 30
       0 1427.57    29.8 1406.55    39.7 1401.58    44.6 1400.22    79.3  1397.5
     114 1399.05   133.9 1397.68   178.5 1399.02   218.1 1398.89   247.9 1393.14
   272.3  1390.1   287.3 1388.95   287.5 1388.94   297.5 1389.55   322.2 1396.31
   327.2 1396.78     347 1395.68   376.8 1396.24   391.6 1395.17   431.4 1394.73
   575.9 1396.45   600.8    1398   655.6 1396.33   675.5  1396.8   685.5 1398.87
   700.4 1404.59   715.4 1408.12   720.3 1411.66   730.3 1421.37   735.3 1424.49
#Mann= 3 , 0 , 0
       0      .1       0   272.3    .045       0   287.3      .1       0
Bank Sta=272.3,287.3
XS Rating Curve= 0 ,0
Exp/Cntr=0.3,0.1

Type RM Length L Ch R = 1 ,219.7   ,220.8,210.9,200.2
XS GIS Cut Line= 3
     1825261.877      198771.885      1825725.32      198779.089
     1826042.286      198692.644
#Sta/Elev= 30
       0 1430.45    39.9 1448.65   104.7 1449.45   119.6 1448.67   149.5 1438.34
   179.4 1416.29   199.4 1402.69   214.3 1398.15   257.4 1389.15   264.1 1388.46
   272.4 1389.45     319 1396.35   373.8 1397.48   413.7 1395.97   453.5 1399.39
   473.4 1399.56   488.4  1400.8   513.3 1399.92   538.2 1402.72   548.1 1402.58
   563.1 1398.52     573 1397.51   602.9 1399.44   627.8 1399.09   652.7 1401.23
   687.5 1401.88   732.3 1398.99   747.2 1400.66   752.2 1403.25     792 1429.28
#Mann= 3 , 0 , 0
       0      .1       0   257.4    .045       0   272.4      .1       0
Bank Sta=257.4,272.4
XS Rating Curve= 0 ,0
Exp/Cntr=0.3,0.1

Type RM Length L Ch R = 1 ,8.8     ,4.2,8.8,23.5
XS GIS Cut Line= 4
     1825408.994      198956.938     1825646.904       198947.96
     1825674.735      198924.618     1825887.507      198814.192
#Sta/Elev= 30
       0 1404.83    14.9 1404.79    29.8 1401.57    54.6 1397.64    74.4 1392.21
    84.3 1390.13    94.2 1388.72     119  1385.9   163.7 1386.01   168.6  1385.5
   193.4 1380.38   208.3 1374.69   213.3 1374.27   218.3 1374.46   233.3 1375.01
   238.1 1375.89   247.2 1379.75   256.2 1382.15   265.3 1383.29   284.4 1384.26
   299.4  1386.2   329.3 1386.83   354.3 1386.67   409.2 1387.52   424.2 1388.27
   449.2  1388.6   464.2 1389.54   479.2 1391.57   494.2 1392.78   514.1  1396.2
#Mann= 3 , 0 , 0
       0      .1       0   218.3    .045       0   233.3      .1       0
Bank Sta=218.3,233.3
XS Rating Curve= 0 ,0
Exp/Cntr=0.3,0.1

Chan Stop Cuts=-1
Use User Specified Reach Order=0